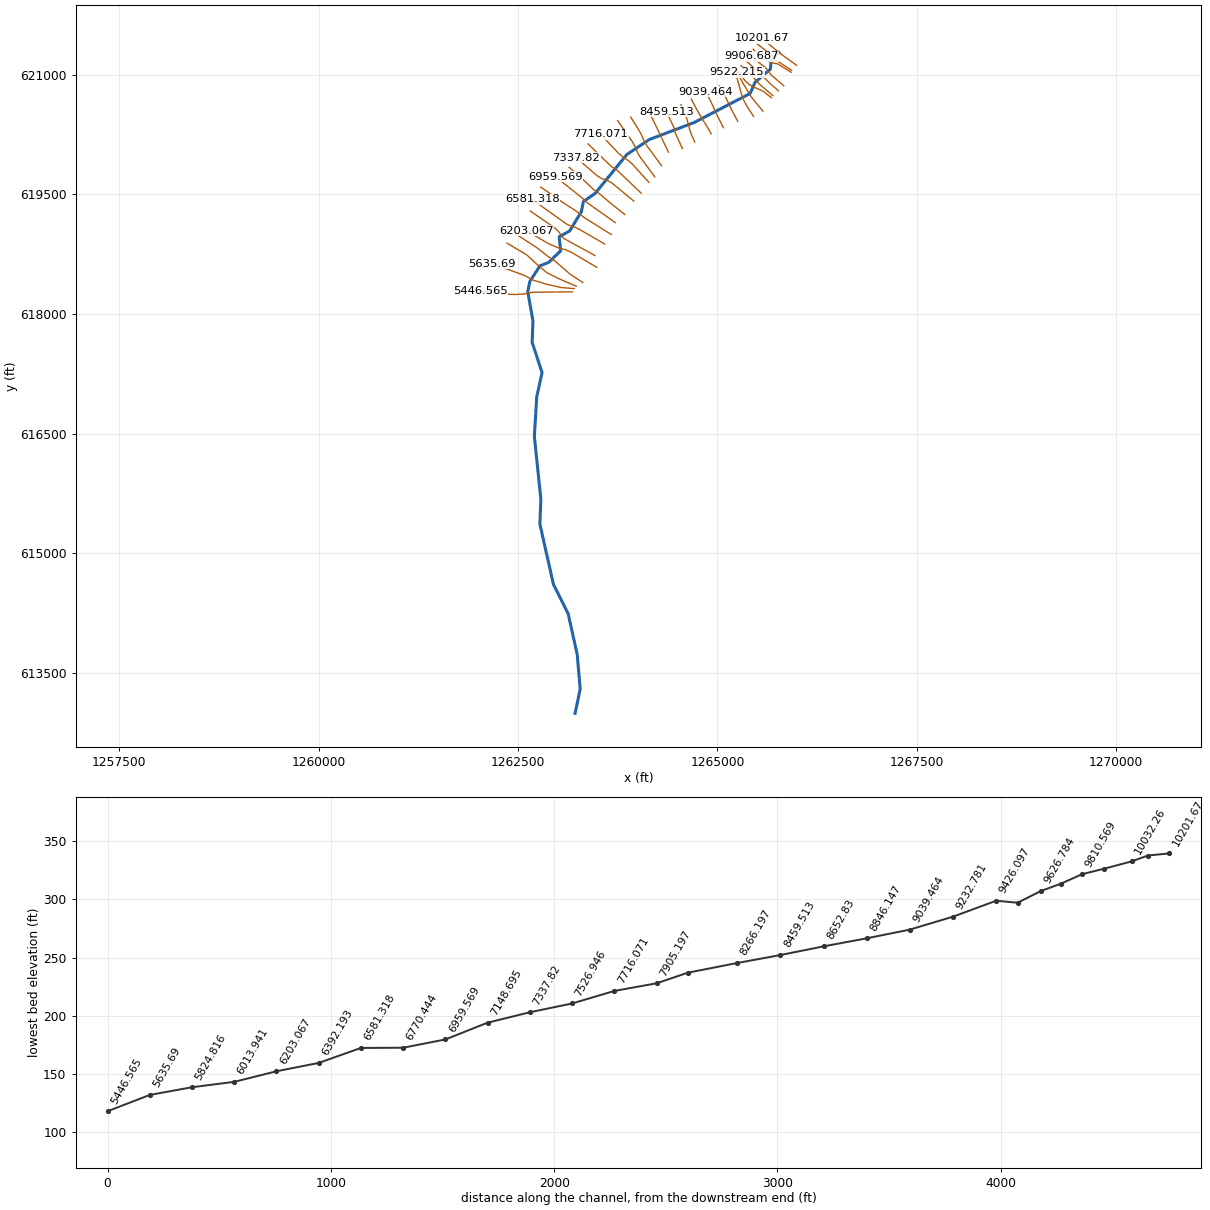
--- 500_ras.prj (project) ---

Proj Title=500
Current Plan=p01
Default Exp/Contr=0.3,0.1
English Units
Geom File=g01
Flow File=f01
Plan File=p01
Y Axis Title=Elevation
X Axis Title(PF)=Main Channel Distance
X Axis Title(XS)=Station
BEGIN DESCRIPTION:
RFD model 500 exported to HEC-RAS
END DESCRIPTION:

--- 500_ras.p01 (plan) ---

Plan Title=Plan 01
Program Version=4.10
Short Identifier=Plan 01
Geom File=g01
Flow File=f01
Subcritical Flow
Calc Critical at every XS
Secant Critical Depth

--- 500_ras.f01 (steady flow) ---

Flow Title=Flow 01
Program Version=5.01
Number of Profiles= 5
Profile Names=10yr,25yr,50yr,100yr,500yr
River Rch & RM=500,45,10201.67
  371.71  441.34   525.6  557.96   650.3
River Rch & RM=500,45,10105.55
   375.4  446.37  531.75  565.32  660.11
River Rch & RM=500,45,10032.26
  460.62  564.32  676.85  741.68  900.33
River Rch & RM=500,45,9906.687
  473.71  582.73  699.59  769.78  939.41
River Rch & RM=500,45,9810.569
  526.72  658.07  792.81  886.15 1103.41
River Rch & RM=500,45,9626.784
  531.04  664.27   800.5  895.82 1117.19
River Rch & RM=500,45,9522.215
  533.72  668.11  805.26  901.82 1125.74
River Rch & RM=500,45,9426.097
  587.16  745.32  901.17 1023.59 1301.09
River Rch & RM=500,45,9232.781
  595.37  757.28  916.05 1042.62 1328.78
River Rch & RM=500,45,9039.464
  656.75  847.42 1028.43 1187.65 1542.04
River Rch & RM=500,45,8846.147
  666.35  861.62 1046.18 1210.74 1576.35
River Rch & RM=500,45, 8652.83
  670.88  868.34 1054.57 1221.68 1592.64
River Rch & RM=500,45,8459.513
  702.07  914.77 1112.63 1297.63  1706.3
River Rch & RM=500,45,8266.197
  709.02  925.16 1125.64 1314.72 1732.01
River Rch & RM=500,45,8045.457
  716.55  936.43 1139.75 1333.28    1760
River Rch & RM=500,45,7905.197
  718.93  939.99  1144.2 1339.14 1768.84
River Rch & RM=500,45,7716.071
   724.3  948.05  1154.3 1352.45 1788.94
River Rch & RM=500,45,7526.946
  764.04 1007.89 1229.35  1451.8 1939.92
River Rch & RM=500,45, 7337.82
  767.11 1012.54 1235.17 1459.55 1951.75
River Rch & RM=500,45,7148.695
  770.16 1017.15 1240.96 1467.25 1963.53
River Rch & RM=500,45,6959.569
  795.36  1055.4 1289.01 1531.33 2061.85
River Rch & RM=500,45,6770.444
  796.81  1057.6 1291.77 1535.03 2067.53
River Rch & RM=500,45,6581.318
  799.69 1061.98 1297.27 1542.39 2078.87
River Rch & RM=500,45,6392.193
  830.08 1108.37 1355.62 1620.68  2199.9
River Rch & RM=500,45,6203.067
  830.89 1109.61 1357.18 1622.78 2203.17
River Rch & RM=500,45,6013.941
  838.42 1121.14 1371.69 1642.32 2233.51
River Rch & RM=500,45,5824.816
  839.49 1122.77 1373.75 1645.09 2237.82
River Rch & RM=500,45, 5635.69
  866.78  1164.7 1426.57 1716.45  2349.1
River Rch & RM=500,45,5446.565
     885 1192.81 1462.01 1764.51 2424.43
River Rch & RM=500,45,5304.384
  888.43 1198.11 1468.69 1773.59 2438.69
River Rch & RM=500,45,5132.595
  889.16 1199.24 1470.12 1775.53 2441.74
River Rch & RM=500,45,4988.907
  893.05 1205.26 1477.71 1785.85 2457.97
River Rch & RM=500,45,4845.219
  894.02 1206.76  1479.6 1788.42 2462.01
River Rch & RM=500,45,4676.201
  894.99 1208.25 1481.48 1790.99 2466.05
River Rch & RM=500,45,4529.254
  896.44 1210.49 1484.31 1794.83 2472.11
River Rch & RM=500,45,4356.385
  941.43 1280.38 1572.56 1915.37 2662.75
River Rch & RM=500,45,4169.147
  943.21 1283.16 1576.08 1920.19 2670.41
River Rch & RM=500,45,4035.494
  943.88 1284.21 1577.39    1922 2673.28
River Rch & RM=500,45,3682.237
  950.08 1293.88 1589.62 1938.78 2699.97
River Rch & RM=500,45,3514.632
  958.84 1307.55 1606.91 1962.52  2737.8
River Rch & RM=500,45,3368.482
  960.36 1309.93 1609.91 1966.65 2744.38
River Rch & RM=500,45,3123.328
  962.95 1313.99 1615.05 1973.71 2755.64
River Rch & RM=500,45,2930.385
  965.11 1317.36 1619.31 1979.57    2765
River Rch & RM=500,45,2674.659
  968.11 1322.06 1625.26 1987.76 2778.07
Boundary for River Rch & Prof#=500,45,1
Up Type= 0
Dn Type= 2
Boundary for River Rch & Prof#=500,45,2
Up Type= 0
Dn Type= 2
Boundary for River Rch & Prof#=500,45,2
Up Type= 0
Dn Type= 2
Boundary for River Rch & Prof#=500,45,2
Up Type= 0
Dn Type= 2
Boundary for River Rch & Prof#=500,45,2
Up Type= 0
Dn Type= 2

--- 500_ras.g01 (geometry) ---

Geom Title=500
Program Version=4.10

River Reach=500,45
Reach XY= 30
 1265770.9329071621282.486346796 1265671.5963107621168.198390499
1265665.09959882621072.4864122271265472.59965077 620906.65313378
1265410.09966505620765.8198440971264709.26652789620402.486639142
1264146.76668766620189.1533856091263865.93343174620002.486782551
1263466.13162419 619512.712398411263318.63166475619410.212433144
1263294.46500152619284.3791378891263146.96503797619041.879214197
  1263015.298408618969.3792395891263035.29839703618794.379290983
1262884.46510389618648.5460053531262774.46513507618604.379355013
1262648.63183323 618410.212749691262621.96517062618281.046122119
1262686.96514064617913.5462293481262676.96513575617644.379642934
 1262801.1317547617266.8797514141262734.46509883616961.879843876
 1262704.4650932 616467.713324861262786.13171262 615676.88022393
1262773.63170728615367.7136494671262943.63163495614611.880535573
1263127.79823655614244.3806393441263241.96485445613731.047455102
1263279.46483073613297.7142493721263215.29817405612992.714341819

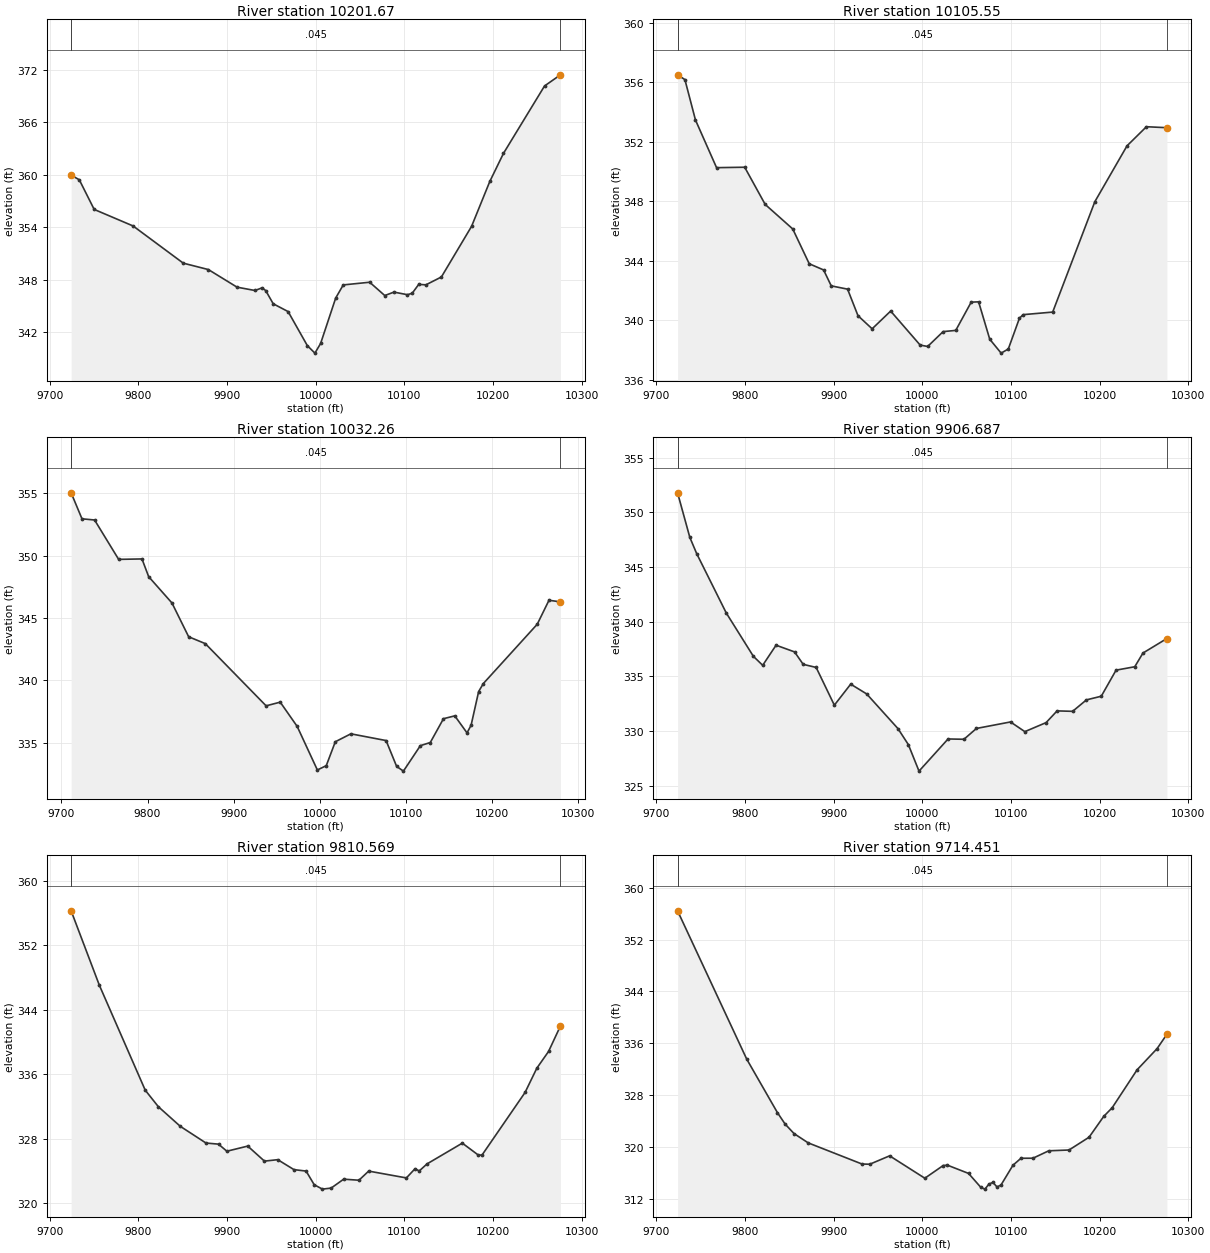
Type RM Length L Ch R = 1 ,10201.67,96.117900,96.117900,96.117900
XS GIS Cut Line= 5
 1265993.3870877621119.3541052311265784.26930852621270.130207703
1265771.02112324621281.0748873081265769.52144757621282.398130628
1265557.62321635621457.673463063
#Sta/Elev= 30
 9724.01359.96099733.218359.43329750.012356.04479793.888354.15399850.514349.9004
9878.826349.16829911.184347.15529931.407 346.7759939.497 347.0829943.541 346.762
9951.963345.25829968.792344.36279990.462340.4732    9999339.614610005.44340.7159
10022.47345.914910030.98347.412510060.79347.720610077.82346.199610088.19346.5914
10103.37346.294310108.78346.462510116.14347.475610124.22347.422810141.69348.3201
10175.75354.109910196.29359.237810211.73 362.45210258.06370.1585   10276371.4322
#Mann= 3 , 0 , 0
 9724.01   0.045       0 9724.01   0.045       0   10276   0.045       0
#XS Ineff= 2 , 0
       09971.353        10044.78       0
Bank Sta=9724.01,10276
Exp/Cntr=0.3,0.1

Type RM Length L Ch R = 1 ,10105.55,73.293800,73.293800,73.293800
XS GIS Cut Line= 6
1265930.43127366621056.7139759331265737.35431436621182.445328543
1265718.31477656621199.5441133361265695.15253196621228.747108798
1265669.72340856621253.0645644451265494.63217946621391.664665857
#Sta/Elev= 30
9724.073356.49179732.352356.17089744.251353.46079768.049350.2586 9799.78350.2876
9822.891347.78959853.977346.14239872.563343.80679888.756343.39179897.399342.3215
9915.807 342.1029927.565 340.3189943.515339.43989964.397340.62989997.686338.3456
10006.15338.253810023.57 339.25110037.81339.332310055.23341.2291 10063.6341.2504
10076.15338.740810088.99337.806310097.08 338.08310109.63340.148610113.81340.3898
10147.14340.562610194.71347.976710230.98351.724710252.86353.007310275.93352.9416
#Mann= 3 , 0 , 0
9724.073   0.045       09724.073   0.045       010275.93   0.045       0
#XS Ineff= 2 , 0
       09962.477        10021.41       0
Bank Sta=9724.073,10275.93
Exp/Cntr=0.3,0.1

Type RM Length L Ch R = 1 ,10032.26,125.569300,125.569300,125.569300
XS GIS Cut Line= 6
1265924.41749123621031.4796404841265755.14665788621137.816446051
1265676.08767217621150.8363987511265596.32490474621188.755805969
1265563.80122229621210.4166492821265448.07200512 621321.19318217
#Sta/Elev= 30
9711.238355.02729723.847352.94519738.494  352.859766.467 349.6959793.588349.7296
9801.337348.31089828.459346.19819847.831343.49399867.204 342.9439937.861337.9591
 9954.27338.25449973.983336.30839997.427332.819310007.77333.163710018.29335.0804
10036.38335.7158 10077.3335.176610089.56333.106410097.44332.726610117.15334.7679
10128.68335.019610144.01336.927510157.15337.155910171.38335.790610176.12 336.406
10184.88339.103810190.36339.7461   10253344.498110266.63346.417310279.96346.2915
#Mann= 3 , 0 , 0
9711.238   0.045       09711.238   0.045       010279.96   0.045       0
#XS Ineff= 2 , 0
       09950.038        10042.16       0
Bank Sta=9711.238,10279.96
Exp/Cntr=0.3,0.1

Type RM Length L Ch R = 1 ,9906.687,96.118000,96.118000,96.118000
XS GIS Cut Line= 6
1265831.89491895620863.2700186391265680.75581232620992.771899407
1265650.28748059621026.549571043 1265615.5091526621075.489143543
1265597.16312463621094.2468991261265422.94079804621230.237457344
#Sta/Elev= 30
9724.056351.78859737.872 347.7179745.603346.23239778.965340.80349809.561 336.839
9820.059336.01599835.144337.85549856.002337.24239865.744336.10429880.356335.8229
 9900.88332.37099919.323334.29359937.351333.39869972.618330.23039984.345328.7656
9996.371326.340210029.13329.281110047.04329.252810061.14330.242710099.57330.8376
10115.73329.951410139.71330.777210152.12331.849110169.63331.8081 10185.2332.8556
10201.92333.188610218.62335.5738 10239.7335.884710248.95337.138110275.93338.4653
#Mann= 3 , 0 , 0
9724.056   0.045       09724.056   0.045       010275.93   0.045       0
#XS Ineff= 2 , 0
       09951.968        10051.59       0
Bank Sta=9724.056,10275.93
Exp/Cntr=0.3,0.1

Type RM Length L Ch R = 1 ,9810.569,96.117900,96.117900,96.117900
XS GIS Cut Line= 6
1265763.68457338620800.227640023 1265659.8183338 620892.37806358
1265562.14115216620987.2035721411265560.76912647620988.658750995
1265492.33991096621055.2649189311265359.19106333621175.644188887
#Sta/Elev= 30
9724.013356.27099755.868347.03069807.584334.01599822.415331.96079847.132 329.529
9876.136327.45359890.266327.31519899.686 326.4379923.237327.07339942.077325.2087
 9957.08325.38839975.371324.15319989.088323.97229998.234322.275810007.47321.7328
10017.33321.862710031.44322.967810048.68322.837710059.66323.970510102.21323.1229
   10112324.270410116.65323.983910125.49324.8632 10165.3327.440410182.99325.9888
10187.41 325.94310236.07333.728510249.34336.7407 10262.6338.821310275.99341.9821
#Mann= 3 , 0 , 0
9724.013   0.045       09724.013   0.045       010275.99   0.045       0
#XS Ineff= 2 , 0
       0 9971.53        10072.47       0
Bank Sta=9724.013,10275.99
Exp/Cntr=0.3,0.1

Type RM Length L Ch R = 1 ,9714.451,87.666600,87.666600,87.666600
XS GIS Cut Line= 6
1265697.25068773   620737.1129391265526.11569824620884.633759975
1265506.21310679 620904.657075241265477.24931705620939.951962065
1265452.16105508620966.3957967341265295.50558176621114.608144173
#Sta/Elev= 30
9724.037356.45149802.065 333.5379836.717325.2678 9845.35  323.51  9855.4322.0444
9871.369320.60569932.011317.34069940.823317.30619963.251318.603810002.95315.1445
10023.65317.107210028.43 317.16110052.27315.888210066.24 313.71310070.76313.4602
10075.27314.243510079.79314.501510084.31313.803110088.82314.085710102.37317.1532
10111.41318.229110124.95318.2369 10142.7319.3807 10165.6319.504610188.19321.4761
10204.76324.699110214.31326.038510242.38331.894310264.97 335.17310275.98 337.379
#Mann= 3 , 0 , 0
9724.037   0.045       09724.037   0.045       010275.98   0.045       0
#XS Ineff= 2 , 0
       09970.414        10032.11       0
Bank Sta=9724.037,10275.98
Exp/Cntr=0.3,0.1

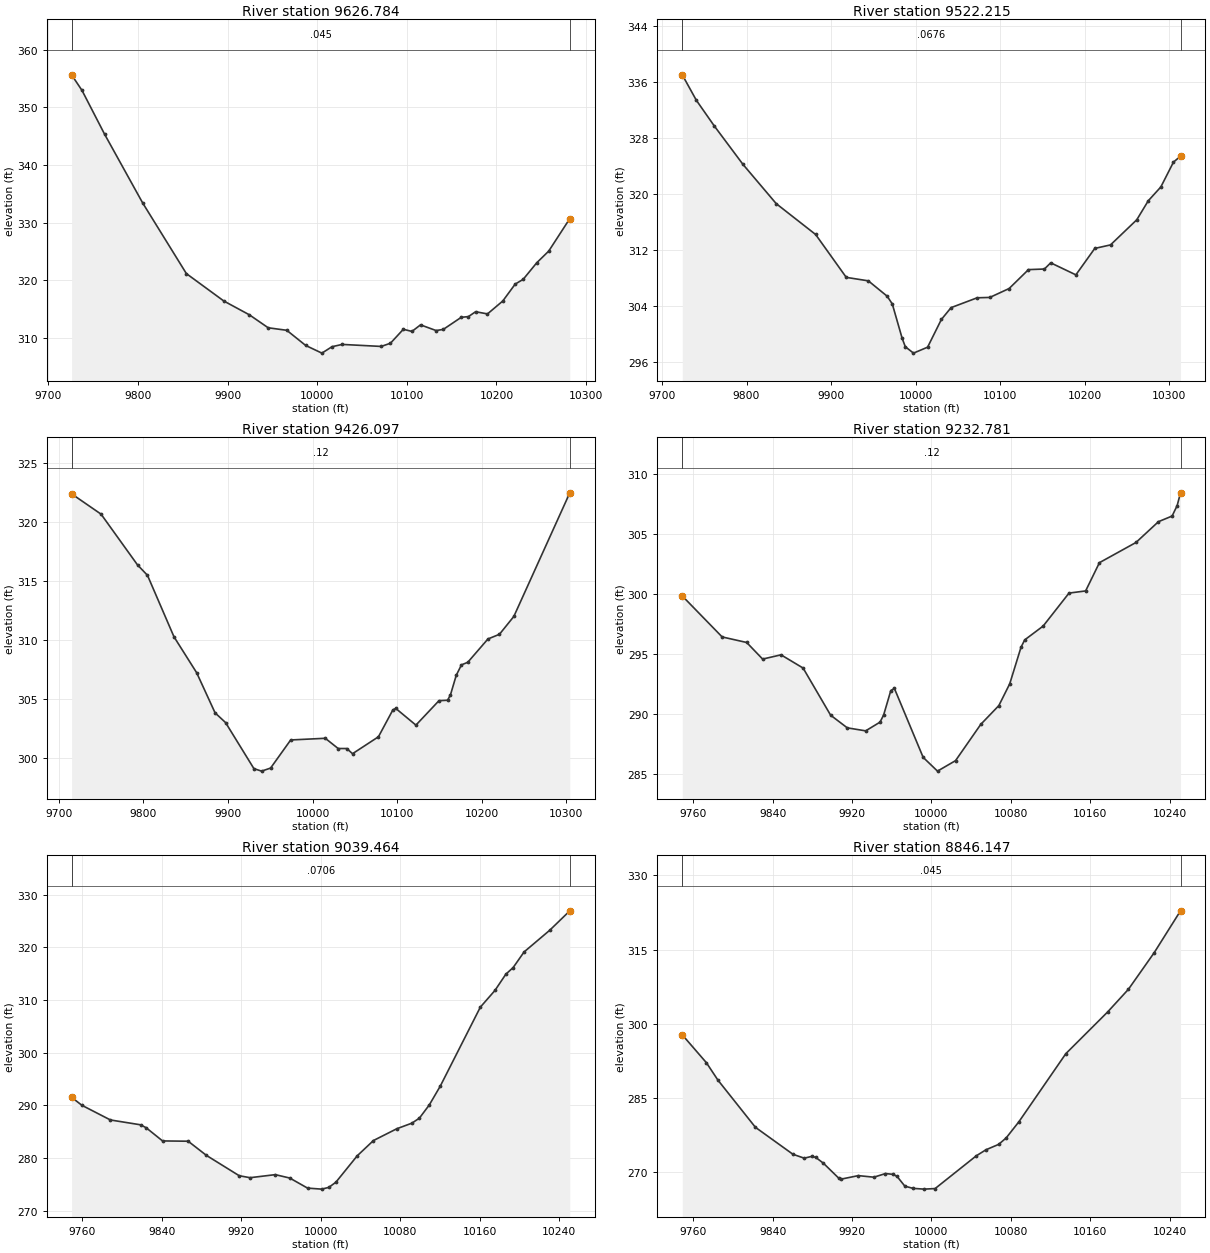
Type RM Length L Ch R = 1 ,9626.784,104.569200,104.569200,104.569200
XS GIS Cut Line= 6
1265675.93658841620713.5542932751265571.79508635620796.165055573
1265443.90723518620851.2307388041265400.55961525620877.903511286
1265345.33639008620926.6730036141265253.84457457621056.436237723
#Sta/Elev= 30
9725.766355.66389737.441 352.9499762.655 345.342 9805.13333.41319853.921321.1449
9895.737316.38419924.333313.97919945.246311.73649966.015311.29849987.092308.6681
10005.21307.334510016.46308.447610027.84308.846510071.39308.496910081.72 309.051
10096.12311.475510105.72311.105510115.31312.243610132.65311.257710140.68311.4526
10160.75313.552710168.78313.679710176.81314.524210190.06314.143710207.14316.3889
10220.97319.321210229.92320.152310245.06323.029910258.39325.047610281.94330.6972
#Mann= 3 , 0 , 0
9725.766   0.045       09725.766   0.045       010281.94   0.045       0
#XS Ineff= 2 , 0
       09966.271        10032.66       0
Bank Sta=9725.766,10281.94
Exp/Cntr=0.3,0.1

Type RM Length L Ch R = 1 ,9522.215,96.117900,96.117900,96.117900
XS GIS Cut Line= 6
1265570.76477593620544.3029708861265432.26018205620713.416922227
1265412.43097723 620740.844799341265394.73089427620772.484540552
1265326.54422733620883.9101960361265246.24908841621033.649779379
#Sta/Elev= 30
9724.035 337.0729740.621333.43549761.824329.7584 9795.75324.25299835.158318.6159
9881.759314.19749918.005 308.0549944.106307.55659966.397305.35389972.445304.2472
9984.062299.34379987.848298.11569997.529297.2011 10014.2298.052810030.48302.0201
10041.98303.719210072.83305.128410087.75305.180510110.63306.455210133.52309.1651
10152.37  309.2510159.82310.1376 10189.6308.415310211.94312.201910230.55312.7051
10261.62 316.30510275.22319.027910290.11321.011710305.01324.563410313.35325.4137
#Mann= 3 , 0 , 0
9724.035  0.0676       09724.035  0.0676       010313.35  0.0676       0
#XS Ineff= 2 , 0
       09950.368        10059.09       0
Bank Sta=9724.035,10313.35
Exp/Cntr=0.3,0.1

Type RM Length L Ch R = 1 ,9426.097,193.316800,193.316800,193.316800
XS GIS Cut Line= 6
1265453.35888806620478.7376228121265384.15573785620584.829744294
1265352.01834124620639.9637037371265331.40887773 620679.58935304
1265307.47906524620736.7216537741265230.11772272621017.843934476
#Sta/Elev= 30
9715.311322.41919750.155 320.6969793.243316.39179804.994 315.5119836.331310.2963
9863.086307.25599884.861303.85449897.264303.0271 9930.77299.1224 9939.83298.9128
9950.459299.17299974.205301.554310015.06301.697210030.28300.829910040.47300.8284
10047.27300.389710077.89301.825110094.93304.102410098.34304.229410122.16302.8124
10149.39304.8839 10159.6304.9219   10163305.385210169.81307.034710175.97 307.921
10183.42 308.13810207.24310.114410220.86310.513110237.87312.026410303.98322.5043
#Mann= 3 , 0 , 0
9715.311    0.12       09715.311    0.12       010303.98    0.12       0
#XS Ineff= 2 , 0
       09938.377        10047.75       0
Bank Sta=9715.311,10303.98
Exp/Cntr=0.3,0.1

Type RM Length L Ch R = 1 ,9232.781,193.316700,193.316700,193.316700
XS GIS Cut Line= 6
1265254.98603939620416.6038432071265168.94623511620580.102211027
 1265140.6283453620641.0559727111265112.63857845620699.989334228
 1265063.5502605620791.6965219441265023.73245793620861.899183875
#Sta/Elev= 30
9749.032 299.8489789.197296.42669813.926295.96379829.978294.57749848.515294.9326
9870.759293.82779898.466289.89499915.248288.83589933.785288.58479948.265289.3136
9951.885289.90849959.125291.94729962.745 292.1259991.705286.371210006.16285.2219
10024.32286.097110049.74289.125710067.95290.694110078.92292.513510090.27295.5599
10093.99296.1793 10112.6297.335710138.65300.088110155.39300.2685 10169.3302.6288
10206.11 304.31410228.74306.050410242.49306.5219 10247.6307.393810250.97308.4603
#Mann= 3 , 0 , 0
9749.032    0.12       09749.032    0.12       010250.97    0.12       0
#XS Ineff= 2 , 0
       09959.086                       0
Bank Sta=9749.032,10250.97
Exp/Cntr=0.3,0.1

Type RM Length L Ch R = 1 ,9039.464,193.316800,193.316800,193.316800
XS GIS Cut Line= 6
1265075.29237991620337.7581515651265004.80168311620475.337712587
1264974.44556356620538.6789138461264952.97468103620589.137393818
1264924.22147723620650.6246305381264854.81171795620788.576821229
#Sta/Elev= 30
9749.013291.53539759.378290.01689788.158287.22669818.561286.30589824.132285.7509
 9840.68283.24379866.484283.18689884.916280.48949917.904276.63129928.819276.2571
9954.286276.83679968.838276.19229986.782274.2777   10001 274.08510008.17274.4146
 10015.3275.397810036.81280.417210053.14283.316710076.65285.556110091.86286.6182
10099.43287.570310109.42290.083610120.44293.643910160.84308.661910175.53311.8293
10186.55314.9273 10193.9316.186510204.92319.153910230.62323.252910250.98326.9655
#Mann= 3 , 0 , 0
9749.013  0.0706       09749.013  0.0706       010250.98  0.0706       0
#XS Ineff= 2 , 0
       09955.618                       0
Bank Sta=9749.013,10250.98
Exp/Cntr=0.3,0.1

Type RM Length L Ch R = 1 ,8846.147,193.316800,193.316800,193.316800
XS GIS Cut Line= 6
1264921.86985285 620260.22136747 1264859.1669976620369.886188213
 1264799.0582312620462.8852090431264791.93781712620475.987528822
 1264729.4131064620586.7345068181264672.17378702620695.388164697
#Sta/Elev= 30
9749.029297.78529773.335292.15069784.929288.63779822.722279.09629860.515  273.65
9871.852 272.8629879.547273.22299883.454273.02579891.267271.83049906.893268.7766
9908.992268.62139926.425 269.3359942.051269.0166 9953.77269.75269961.583269.5832
 9965.49269.15879973.303267.2015 9981.52266.76029992.544 266.60510003.76266.7187
10045.21273.331410054.88274.545910067.81275.650110075.35276.951910088.25280.2397
10135.51293.990510177.57302.403910198.55306.995510224.51 314.39510250.99322.8435
#Mann= 3 , 0 , 0
9749.029   0.045       09749.029   0.045       010250.99   0.045       0
#XS Ineff= 2 , 0
       09953.789                       0
Bank Sta=9749.029,10250.99
Exp/Cntr=0.3,0.1

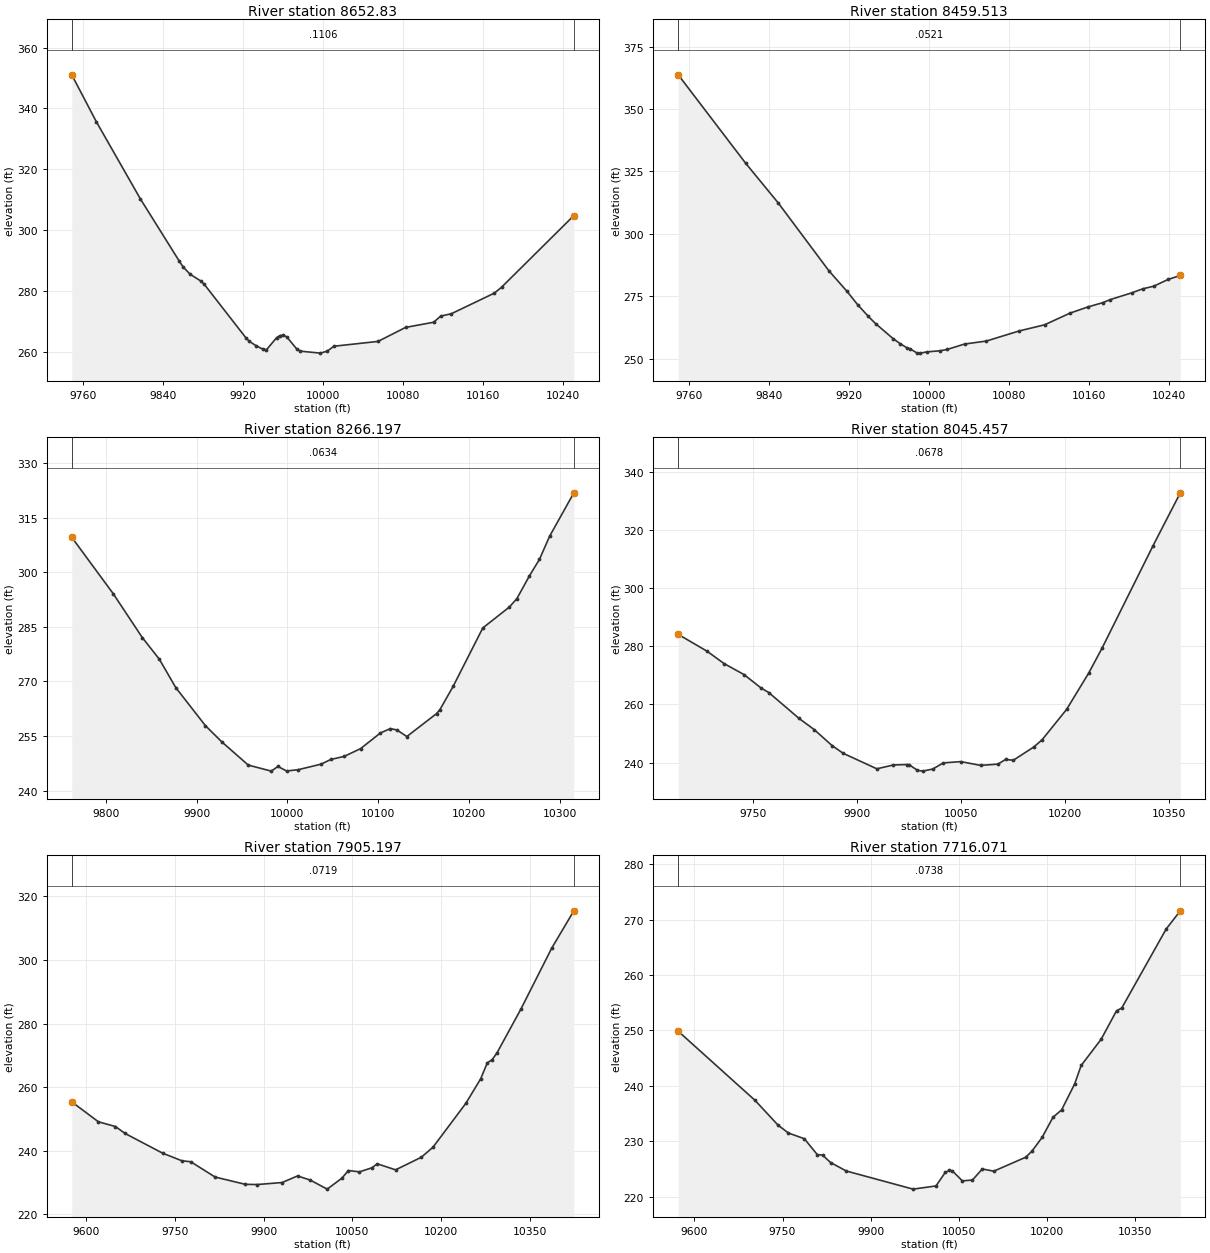
Type RM Length L Ch R = 1 , 8652.83,193.316700,193.316700,193.316700
XS GIS Cut Line= 6
1264716.55175152620156.786953785 1264681.8218683620233.179789191
1264656.00545308620299.1564876311264620.78605607620436.421863812
1264605.06681716620484.8984494591264542.32485373620625.963488813
#Sta/Elev= 30
9749.036351.05059773.581335.66039817.605310.32169856.703289.76619860.227288.0307
9867.273 285.5799877.842283.38499881.365282.31649923.106264.69379926.534263.5255
 9933.39262.07319940.246260.91979943.674260.74579953.886264.76039957.252 265.428
9960.618265.55239963.984 264.9839974.082260.96919977.448260.30989997.643259.6574
10004.39260.316310011.14261.920110055.21263.5063 10082.8268.105510110.79 269.801
10117.88271.812610128.52   272.610171.41 279.34710178.65  281.2810250.97304.8337
#Mann= 3 , 0 , 0
9749.036  0.1106       09749.036  0.1106       010250.97  0.1106       0
#XS Ineff= 2 , 0
       0                10062.88       0
Bank Sta=9749.036,10250.97
Exp/Cntr=0.3,0.1

Type RM Length L Ch R = 1 ,8459.513,193.316800,193.316800,193.316800
XS GIS Cut Line= 6
1264561.27435534620076.2577264261264477.00807544620258.676864544
1264467.43766303620287.2234866191264460.82253762620323.118376728
 1264453.4291943620342.9700335561264361.20374688620535.158909157
#Sta/Elev= 30
9749.043363.67849816.489328.24089849.053312.34499899.657285.18499917.597277.0224
9928.362271.62779939.126266.90739946.302264.03319963.735258.04999970.656256.0591
9977.576254.35479981.003253.8702 9987.67252.28519991.003252.2049 9997.67252.7065
10011.02253.155610018.02253.690110035.26255.8411   10057257.038210090.09261.1139
10115.22263.5397 10140.7268.222110158.34270.674610173.45272.421810180.72273.6228
10202.56276.373110213.48 277.97110224.39 279.01410238.95281.749610250.96283.3179
#Mann= 3 , 0 , 0
9749.043  0.0521       09749.043  0.0521       010250.96  0.0521       0
#XS Ineff= 2 , 0
       0                10083.96       0
Bank Sta=9749.043,10250.96
Exp/Cntr=0.3,0.1

Type RM Length L Ch R = 1 ,8266.197,220.739700,220.739700,220.739700
XS GIS Cut Line= 5
1264385.09905991620030.3561074581264284.50642666620244.179561168
 1264283.3554399620245.8151740431264181.08599347620460.675207734
1264146.11325368620528.381236076
#Sta/Elev= 30
9762.696309.61089808.245294.13889840.301282.05729859.005276.12999877.134268.3119
9909.766257.84289927.895253.36499956.901247.01449982.281245.35079989.533246.6453
    9999245.3969 10011.5245.725910036.94247.263810047.84248.565310062.51249.4073
10080.54251.540810102.34255.843410113.24257.045310120.51256.663810131.41254.8613
10164.11261.164310167.74262.232510182.28268.620210214.98284.698310244.13290.4288
10252.44292.746910266.29299.022610277.36303.565310288.44309.883410315.16321.8363
#Mann= 3 , 0 , 0
9762.696  0.0634       09762.696  0.0634       010315.16  0.0634       0
#XS Ineff= 2 , 0
       0                10067.79       0
Bank Sta=9762.696,10315.16
Exp/Cntr=0.3,0.1

Type RM Length L Ch R = 1 ,8045.457,140.260300,140.260300,140.260300
XS GIS Cut Line= 6
1264299.41478866619861.3810410351264116.69403231 620108.72839658
1264085.04729581620161.6448833641264046.78207731620250.146021739
1264016.99981469 620303.480207921263912.84341714620470.100878924
#Sta/Elev= 30
9642.598284.05169683.977278.28229708.641274.02099737.417270.22629762.135265.5866
9773.025264.06849816.587 255.1829838.368 251.3579864.335245.8087 9880.43243.1591
9928.717237.85519952.724239.17769971.838239.31539975.661 239.1929987.129237.3493
9994.775237.057210009.33237.778410024.51239.8838 10049.6240.324510078.18239.0371
10103.13239.454310114.13241.0671 10125.4240.8003   10155245.379610166.73247.8018
10202.07  258.2510233.75270.663110253.28279.3542 10326.5314.451910365.94332.6909
#Mann= 3 , 0 , 0
9642.598  0.0678       09642.598  0.0678       010365.94  0.0678       0
#XS Ineff= 2 , 0
       0                10061.79       0
Bank Sta=9642.598,10365.94
Exp/Cntr=0.3,0.1

Type RM Length L Ch R = 1 ,7905.197,189.125500,189.125500,189.125500
XS GIS Cut Line= 6
1264214.77937199619720.7560410311264032.05861565619968.103396583
1264000.41187915620021.0198833711263962.14666064620109.521021737
  1263932.364398620162.8552079081263748.53294058620426.591558516
#Sta/Elev= 30
9575.885255.3505 9620.81249.08929649.585 247.5999666.028245.40669729.199239.2299
 9761.87236.8223 9776.95236.51139818.054231.70189869.053229.41219889.309229.3449
 9931.36229.98469957.305232.05299978.809 230.74710007.41227.902110032.36231.3523
10043.14233.758710061.93233.337410082.92234.615410091.99235.870210122.99233.9709
10166.33237.921210186.03241.060110241.59254.871510266.76 262.61210277.93267.6359
10286.01268.602210294.08270.695810334.46284.459310386.94303.779110424.13315.4464
#Mann= 3 , 0 , 0
9575.885  0.0719       09575.885  0.0719       010424.13  0.0719       0
#XS Ineff= 2 , 0
       09872.369        10067.15       0
Bank Sta=9575.885,10424.13
Exp/Cntr=0.3,0.1

Type RM Length L Ch R = 1 ,7716.071,189.125500,189.125500,189.125500
XS GIS Cut Line= 6
1264140.29313839 619652.031137291263939.59146128619874.307780664
1263885.26243502619923.3777864571263808.43558475619975.297126683
1263759.12039152620017.0879079031263535.73383821620253.312419024
#Sta/Elev= 30
9572.313249.84959703.089237.37579742.485232.88099759.994231.4731 9787.16230.4408
9809.214227.5738 9818.24227.4869 9831.78226.14349858.826224.6057 9972.38221.3416
10011.43 221.91810027.19224.357110033.95224.709610039.13224.657410056.33222.8316
10073.53222.982410090.32224.9803 10109.9224.582210164.24227.100410174.65228.1667
10192.17230.673310210.79234.322310225.44235.650510247.71240.348410258.76243.6735
10292.72248.390410318.98253.543410327.89254.042610403.62268.319410427.65271.5907
#Mann= 3 , 0 , 0
9572.313  0.0738       09572.313  0.0738       010427.65  0.0738       0
#XS Ineff= 2 , 0
       09871.157         10040.8       0
Bank Sta=9572.313,10427.65
Exp/Cntr=0.3,0.1

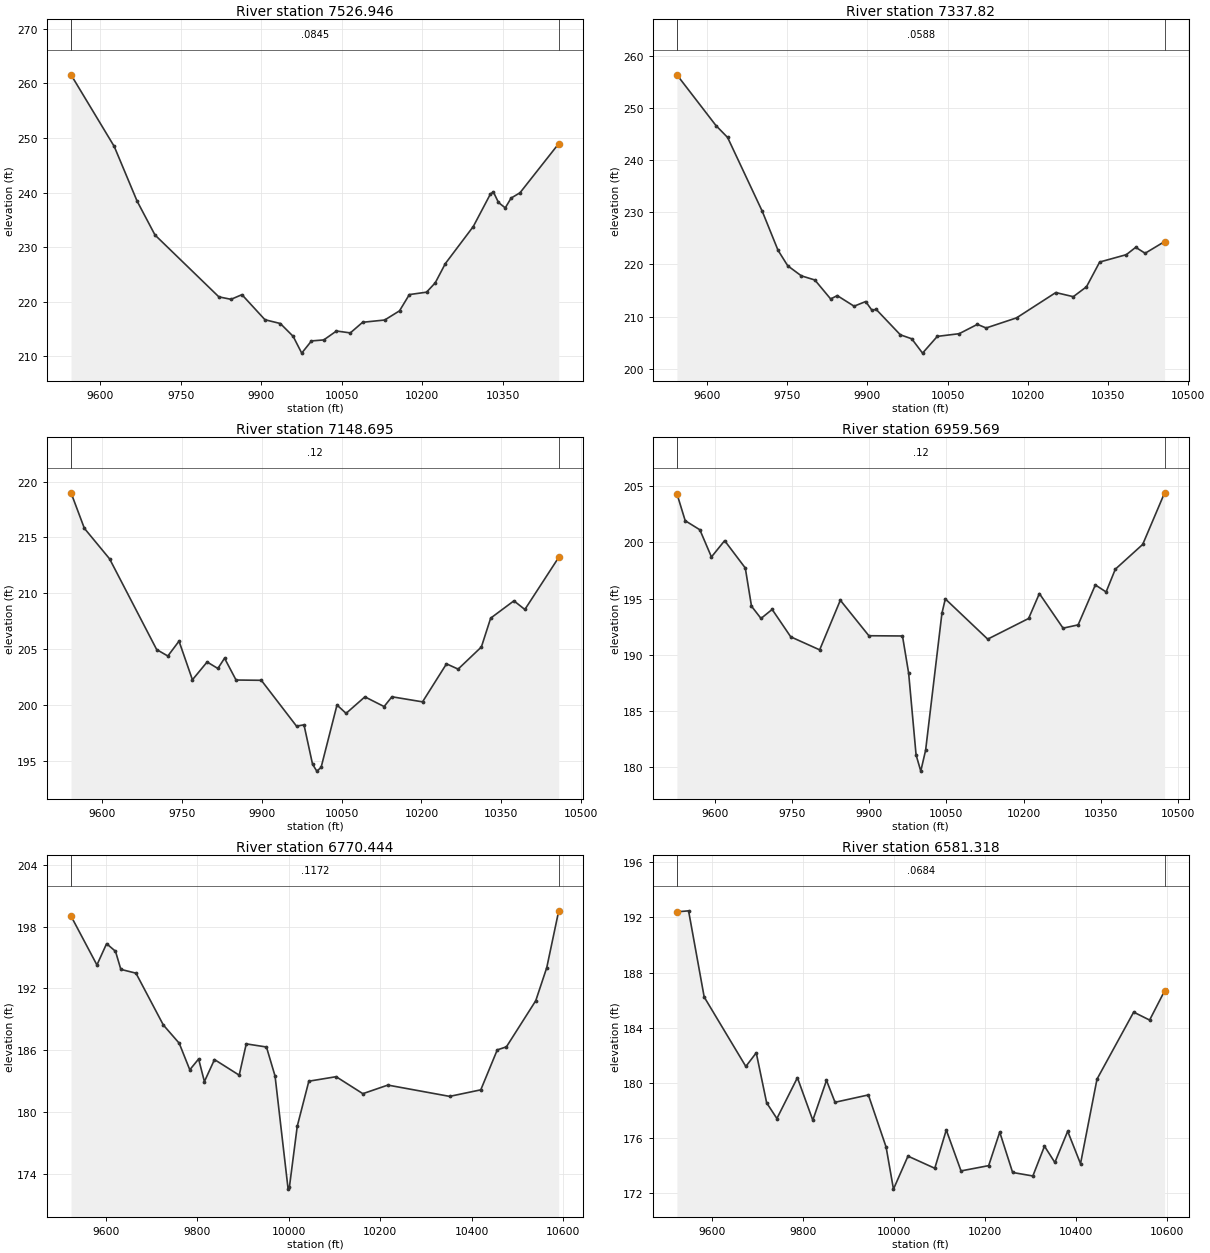
Type RM Length L Ch R = 1 ,7526.946,189.125500,189.125500,189.125500
XS GIS Cut Line= 6
1264042.85360454619517.6977897521263744.06428489619801.955480483
1263722.38520166619818.9560592661263688.74231329619835.846384613
1263658.18025441619861.3408571711263378.47198629620133.403886955
#Sta/Elev= 30
 9546.17261.58379626.561248.45059669.075238.43579702.394232.22269821.281220.8786
9843.923220.42959864.229221.27959907.068216.68639935.627215.99449959.527213.6446
9975.477210.56369993.664212.8016 10016.5212.982710040.16214.619910065.95214.2705
10088.83216.217510129.89216.634210157.49218.315710175.79221.296310207.83221.7387
   10224223.451110242.82226.982110294.79233.773710326.83239.759510332.22240.1099
10341.63238.192410354.29237.187310365.16238.986210381.75 239.95910453.84248.9694
#Mann= 3 , 0 , 0
 9546.17  0.0845       0 9546.17  0.0845       010453.84  0.0845       0
#XS Ineff= 2 , 0
       09924.931        10060.38       0
Bank Sta=9546.17,10453.84
Exp/Cntr=0.3,0.1

Type RM Length L Ch R = 1 , 7337.82,189.125600,189.125600,189.125600
XS GIS Cut Line= 6
 1263951.4579474619416.8943602941263681.53746319619640.136543433
1263620.54734887619676.3177107571263544.63396894619700.777093327
1263486.43640432 619739.091461181263229.07883439619962.053715822
#Sta/Elev= 30
9544.137256.36359617.218246.62739638.846244.3633 9703.73 230.1919733.153222.7284
9751.311 219.7529776.701217.82849802.018217.02929831.556213.39169843.847214.0383
9875.355 212.0069896.975212.89719908.729211.22959916.565211.40239961.804 206.522
9983.105205.756710003.33203.008410030.91206.220210071.77206.733110105.83208.5246
10122.19207.831210179.02209.766110252.41214.621210285.15213.8305 10309.8215.7285
10334.45220.471510384.26221.885810401.84223.294810419.42222.154710455.84224.3996
#Mann= 3 , 0 , 0
9544.137  0.0588       09544.137  0.0588       010455.84  0.0588       0
#XS Ineff= 2 , 0
       09930.468        10083.95       0
Bank Sta=9544.137,10455.84
Exp/Cntr=0.3,0.1

Type RM Length L Ch R = 1 ,7148.695,189.125500,189.125500,189.125500
XS GIS Cut Line= 6
1263837.98786203619248.8908737091263656.91949795619393.320568299
1263519.53795656619510.7555202291263448.58209327619561.153663843
1263301.11769816619700.2320924851263140.54092295619841.217695214
#Sta/Elev= 30
  9542.1218.98639567.109215.80699614.461213.07229702.873204.94639723.857204.3673
 9744.84 205.701 9770.02202.23839797.604203.83379817.801 203.2529830.341204.1741
9851.922202.21819899.399 202.1929965.484198.08739979.513198.20329995.565194.6806
10003.54194.056610011.63194.386410041.49199.980110058.58 199.23210093.88200.7105
10129.96 199.84110144.65200.717510202.12200.261710247.12203.668310268.95203.1949
10312.61205.176610330.07207.761310373.73209.310610394.28 208.53610457.88213.2066
#Mann= 3 , 0 , 0
  9542.1    0.12       0  9542.1    0.12       010457.88    0.12       0
#XS Ineff= 2 , 0
       0 9940.44        10067.41       0
Bank Sta=9542.1,10457.88
Exp/Cntr=0.3,0.1

Type RM Length L Ch R = 1 ,6959.569,189.125500,189.125500,189.125500
XS GIS Cut Line= 6
1263719.18246824 619146.891945911263365.79933382619397.309457937
1263346.74003164  619413.31649911263311.16947179619448.943462641
1263274.48128397619480.166278865 1262966.9825296619724.462640143
#Sta/Elev= 30
9525.374204.33599541.505201.92899569.998201.12159592.575198.70029618.251200.1542
9658.461197.71659670.525194.31689689.041193.22399710.735194.02749746.925191.5867
 9803.22190.42689843.431194.84749898.995191.68489964.428191.66269976.422188.3519
9990.889181.069710000.03179.626410009.47181.4928 10041.2193.684810047.79194.9649
10130.31191.382110209.92193.221410230.87195.442510276.97192.3596 10306.3192.6514
10339.82196.209110360.77195.583810378.63197.6068   10432199.817710474.63204.4122
#Mann= 3 , 0 , 0
9525.374    0.12       09525.374    0.12       010474.63    0.12       0
#XS Ineff= 2 , 0
       09935.736        10061.11       0
Bank Sta=9525.374,10474.63
Exp/Cntr=0.3,0.1

Type RM Length L Ch R = 1 ,6770.444,189.125500,189.125500,189.125500
XS GIS Cut Line= 6
1263669.52185777618997.8068911281263340.83832097619203.545930073
1263306.47545022619228.1461284911263224.21693459619294.594170257
1263058.62757486619400.820454016 1262785.3332898619592.380971506
#Sta/Elev= 30
9524.419 199.0119581.009194.26949602.123196.33629621.588195.59689633.266193.8428
9666.345193.47429726.174188.44379760.892186.67379784.037184.09399803.325185.1424
9815.977182.95019838.043185.08799892.049183.57229907.479186.61039951.646 186.307
9970.468 183.485    9999172.510410001.86172.7179   10019178.623310044.31182.9868
10103.98183.424610162.42181.776210217.11182.610210352.13181.513610420.24182.1486
 10456.3186.026110476.33186.324910540.44190.801310564.48194.011110590.68199.5255
#Mann= 3 , 0 , 0
9524.419  0.1172       09524.419  0.1172       010590.68  0.1172       0
#XS Ineff= 2 , 0
       09933.947        10079.62       0
Bank Sta=9524.419,10590.68
Exp/Cntr=0.3,0.1

Type RM Length L Ch R = 1 ,6581.318,189.125500,189.125500,189.125500
XS GIS Cut Line= 6
1263586.70318231 618878.371209011263271.05189285619061.194906011
1263206.86890945619092.0790168341263144.59292635619110.998781428
1263106.94059363619129.873426408 1262675.9582898619437.867082611
#Sta/Elev= 30
9522.532192.40429548.179192.4785 9582.54186.23329674.169181.20099697.077182.1891
 9719.92178.56889742.496177.42799787.649180.38669821.513177.30539851.615180.1919
9870.429 178.6069943.794179.13839982.807175.3604    9999172.312510030.93174.7042
10089.91173.8241 10115.2176.597310147.64 173.63210208.48174.015110232.81176.4447
 10261.2173.519510305.72173.265310331.32175.426210354.11174.242410382.35 176.507
10410.58174.151110446.87180.284610527.53185.138910562.62184.5628 10595.6186.6765
#Mann= 3 , 0 , 0
9522.532  0.0684       09522.532  0.0684       0 10595.6  0.0684       0
#XS Ineff= 2 , 0
       0 9940.56        10051.07       0
Bank Sta=9522.532,10595.6
Exp/Cntr=0.3,0.1

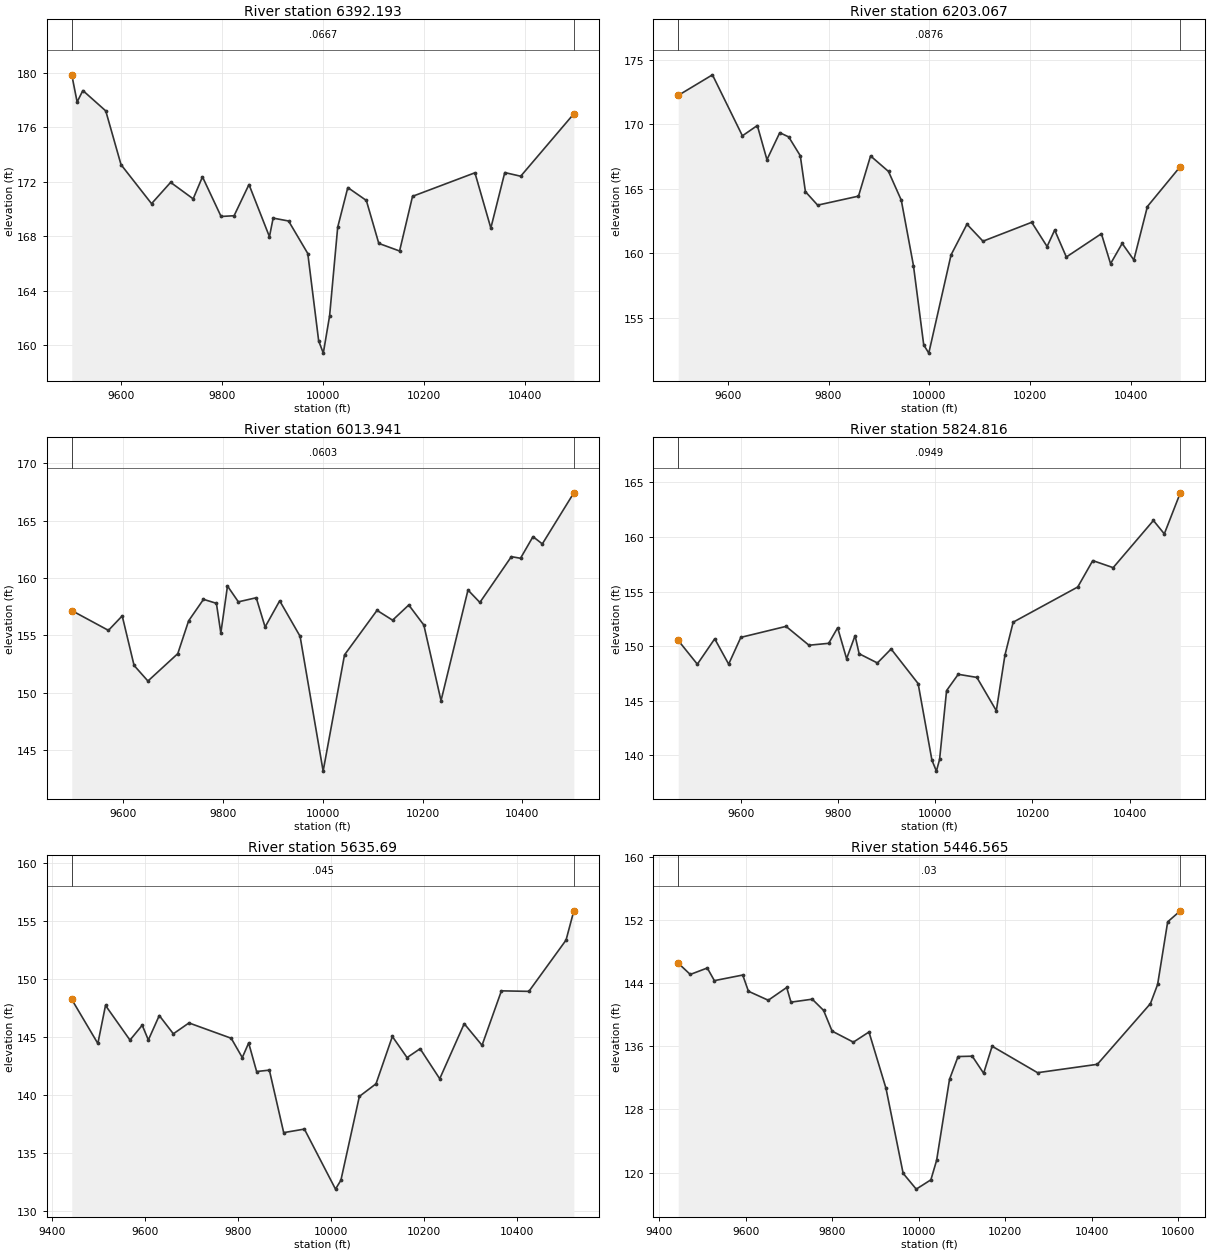
Type RM Length L Ch R = 1 ,6392.193,189.125500,189.125500,189.125500
XS GIS Cut Line= 6
1263465.61912292618733.1436147521263077.69734856618946.314638983
1263054.62068223618966.936672361 1263010.9381743619032.805695942
1262961.09567166619079.9413862641262653.54257889619292.133013175
#Sta/Elev= 30
9502.337 179.8549512.971177.86069524.319 178.7039569.712177.20649599.974173.2632
9660.497170.40049698.324171.96359743.011170.7544 9761.45172.36929798.329169.4604
9824.144169.51439853.647171.80429894.214167.97619901.589169.34139932.167169.1271
9970.243166.74089991.822 160.329   10001159.4321 10013.5162.1684 10029.5168.6641
10049.57171.581910086.33170.635310111.01167.4835 10152.2166.926610177.89170.9381
10301.58172.665610333.14168.610710360.76172.682410392.32172.4134 10497.7176.9961
#Mann= 3 , 0 , 0
9502.337  0.0667       09502.337  0.0667       0 10497.7  0.0667       0
#XS Ineff= 2 , 0
       09894.053        10064.52       0
Bank Sta=9502.337,10497.7
Exp/Cntr=0.3,0.1

Type RM Length L Ch R = 1 ,6203.067,189.125600,189.125600,189.125600
XS GIS Cut Line= 6
1263486.76669536618586.4270105631263171.29948513618773.494222941
1263093.82261425618807.6597360641262995.82424532618833.879255595
1262883.93840507618881.5296054361262606.75312829619044.540924774
#Sta/Elev= 30
9501.751172.22959569.655173.82359629.099169.09639658.728169.89459677.815167.2467
9703.264169.33849721.001169.01119743.976 167.5539754.163 164.7699778.439163.7225
9859.526164.42049883.475167.53699919.106166.33249944.441164.10889968.604159.0377
9988.998152.89029999.033152.252210043.24159.867710074.78162.243610106.61160.9278
10203.33162.392710233.84160.514410248.91161.790610272.05159.703610341.64161.5096
10359.81159.1811 10382.9160.7561   10406159.472810432.94163.616710498.26166.7159
#Mann= 3 , 0 , 0
9501.751  0.0876       09501.751  0.0876       010498.26  0.0876       0
#XS Ineff= 2 , 0
       09947.622        10088.62       0
Bank Sta=9501.751,10498.26
Exp/Cntr=0.3,0.1

Type RM Length L Ch R = 1 ,6013.941,189.125500,189.125500,189.125500
XS GIS Cut Line= 6
1263312.90835562618396.2808906891263158.71850736618495.332926998
1262958.06130951618669.4537282211262867.16966541 618729.13531271
1262733.13698211618834.6517498071262500.07990333  618985.9934375
#Sta/Elev= 30
9496.754157.1592 9570.26155.43559597.858156.6974 9621.66152.38189649.429151.0213
9709.272153.40829730.979156.2648 9760.82158.13839786.713157.79229795.584 155.199
 9808.89159.29979830.693157.92129866.551158.27719884.321155.72969913.572158.0115
9954.453154.918310000.66 143.17310043.52153.300410108.67157.178610139.89156.3235
10172.32157.646110202.53155.899110236.99149.311410291.05 158.94910314.89157.8682
10377.98161.857510396.35161.717410421.33163.599310440.07162.968410503.24167.4179
#Mann= 3 , 0 , 0
9496.754  0.0603       09496.754  0.0603       010503.24  0.0603       0
#XS Ineff= 2 , 0
       09913.805         10079.1       0
Bank Sta=9496.754,10503.24
Exp/Cntr=0.3,0.1

Type RM Length L Ch R = 1 ,5824.816,189.125500,189.125500,189.125500
XS GIS Cut Line= 6
1263229.97304675618348.8262840061263004.71263012618446.482534021
1262864.08763012618518.097117335 1262774.5808906618589.069212213
1262611.11818874618740.735761046  1262361.228542618889.840828657
#Sta/Elev= 30
9471.742150.51519511.027148.3361 9546.75150.66589575.393148.34199600.424150.7971
9693.397151.80499740.553150.07589781.053150.25089799.462151.6771 9817.87148.8417
9835.306150.95469843.643149.2963  9881.2148.44959909.393149.73279964.941146.5595
 9993.28139.542310002.49138.530610009.04139.600410023.42145.912910047.39147.4099
10085.72147.124810125.67144.073210143.43149.168910160.34152.1903 10293.1155.4167
10323.95157.836710365.93157.190610448.66161.515210471.07160.287410503.96164.0517
#Mann= 3 , 0 , 0
9471.742  0.0949       09471.742  0.0949       010503.96  0.0949       0
#XS Ineff= 2 , 0
       09913.369        10052.55       0
Bank Sta=9471.742,10503.96
Exp/Cntr=0.3,0.1

Type RM Length L Ch R = 1 , 5635.69,189.125500,189.125500,189.125500
XS GIS Cut Line= 6
1263203.93138009 618318.878367351263038.56679675618333.201284006
1262861.48346344 618373.565867351262699.40043259618422.508175865
1262576.51639515618485.748868555 1262177.4246614618632.167275131
#Sta/Elev= 30
9441.573148.23769497.716144.44419514.181147.72199566.871144.73669593.216146.0195
9606.389144.74479629.918146.85399660.203145.27979693.853146.21469784.707144.8963
9808.615143.23219822.323144.49049839.459142.03029866.876142.1512 9897.72 136.767
9942.273137.072910009.22131.901610020.83132.6666 10060.6139.887110096.41140.9729
10131.58145.049910163.22143.230710191.35143.993810233.54141.407210286.27146.1499
10324.64144.289610366.36148.979410425.47148.933810505.43153.350410522.23155.8706
#Mann= 3 , 0 , 0
9441.573   0.045       09441.573   0.045       010522.23   0.045       0
#XS Ineff= 2 , 0
       09889.951        10128.75       0
Bank Sta=9441.573,10522.23
Exp/Cntr=0.3,0.1

Type RM Length L Ch R = 1 ,5446.565,142.181100,142.181100,142.181100
XS GIS Cut Line= 6
1263182.37466711618278.6946289091262686.55659437618274.096182182
1262570.37606686 618250.661228851262458.97226065618245.108609125
1262283.34046432618254.2023124691262026.65273425618290.297638178
#Sta/Elev= 30
9443.829146.56839471.645145.13949511.016145.9586 9527.42144.35449593.038145.0661
9606.162143.00759652.094141.86559694.746 143.4869704.588141.62299753.802142.0005
9780.049140.57759799.734137.94689848.948136.54749885.038137.83419924.432130.6774
9964.048119.89719994.367117.891210028.22119.071410041.53121.551510071.34131.8281
 10091.1134.720410123.98134.763710150.23132.595110169.92136.029410275.01132.6693
10413.34133.734210536.07141.4372 10552.7143.867110575.98151.8177 10605.2153.2147
#Mann= 3 , 0 , 0
9443.829    0.03       09443.829    0.03       0 10605.2    0.03       0
#XS Ineff= 2 , 0
       09893.611        10096.59       0
Bank Sta=9443.829,10605.2
Exp/Cntr=0.3,0.1