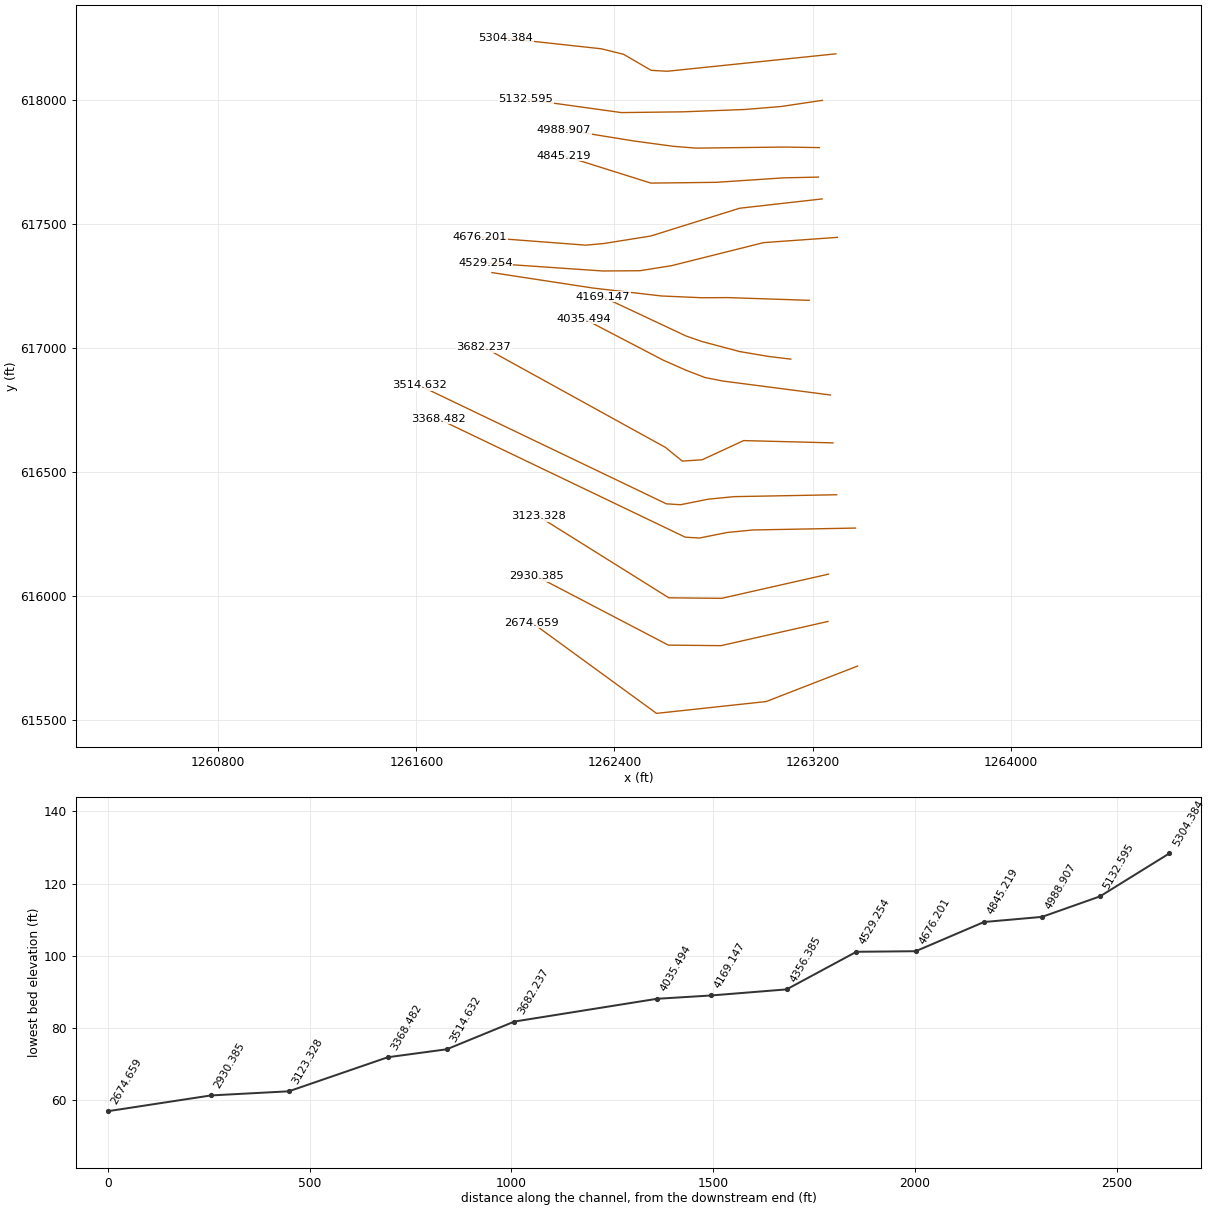
HEC-RAS study 500_ras.prj: 500

--- 500_ras.g01 (geometry) --- (continued)

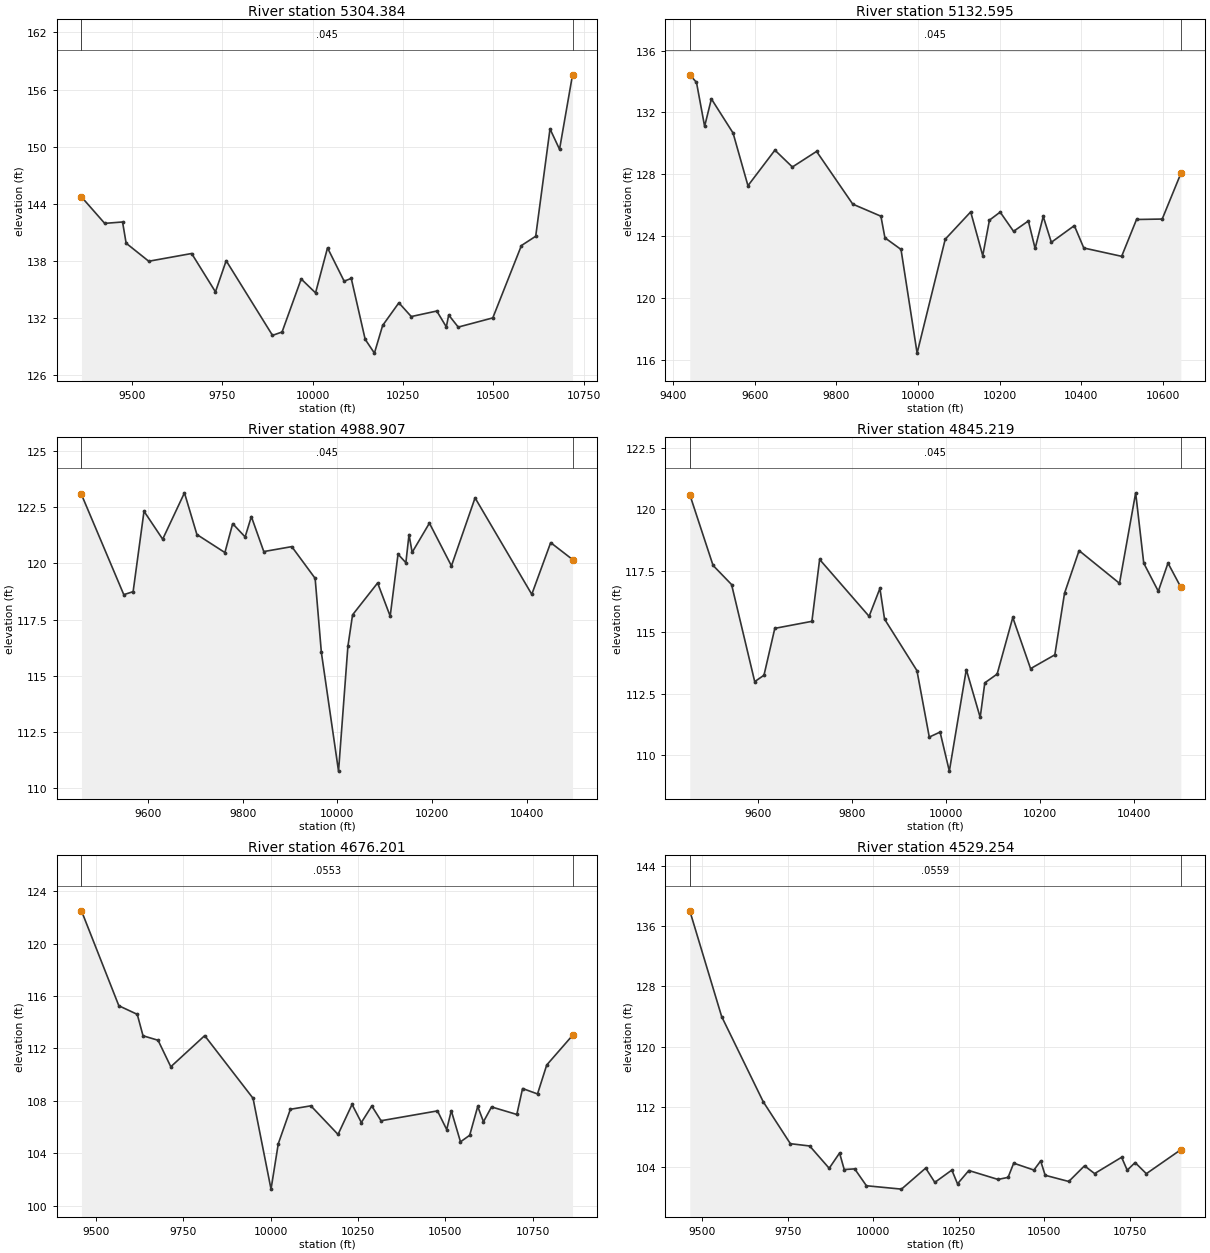
Type RM Length L Ch R = 1 ,5304.384,171.788600,171.788600,171.788600
XS GIS Cut Line= 6
1263294.01384535618187.8670826111262613.28978974618117.478900179
1262548.26008382618121.1425455961262436.57026902 618186.06586735
1262346.72651899618208.2012840061261960.68051207618250.367082611
#Sta/Elev= 30
9359.587144.72489423.912141.94839473.378142.09439483.271139.86699545.929137.9728
9664.648138.78489730.603134.75929760.283138.02839888.561130.1917 9915.05130.5434
9968.038 136.11210007.78134.650310040.93 139.37810086.96135.881410106.68136.1695
10145.16129.778210170.78128.326810193.55131.2314 10238.5133.609210272.81132.1668
10343.48132.746910369.88131.081410376.48132.326110402.88131.060710498.59132.0259
 10577.8139.6199 10617.4140.596810657.01151.864410683.41149.722910719.37157.5426
#Mann= 3 , 0 , 0
9359.587   0.045       09359.587   0.045       010719.37   0.045       0
#XS Ineff= 2 , 0
       09932.045         10136.3       0
Bank Sta=9359.587,10719.37
Exp/Cntr=0.3,0.1

Type RM Length L Ch R = 1 ,5132.595,143.688300,143.688300,143.688300
XS GIS Cut Line= 6
1263239.66633382618000.0487955811263074.30175048617975.309212267
1262926.50957456  617963.0955358 1262676.8397308617953.648006991
1262428.46841711617950.5696289091262043.05175045618003.955045596
#Sta/Elev= 30
9440.997134.43179457.386133.94389477.291131.10059493.877 132.8769546.955130.6682
9583.446127.26069649.475129.56039692.271128.47039751.528129.47849840.177126.0685
9909.115125.28879918.964 123.8919958.365123.13699997.779116.432310066.69 123.801
10129.03125.567110158.56122.734610174.97125.033310201.22125.553210234.03 124.309
10270.26124.980910286.83123.2003 10306.7 125.27310326.57123.599810382.88124.6786
10406.06123.2321 10498.8122.693210535.24125.075310598.17125.104410643.84128.0533
#Mann= 3 , 0 , 0
9440.997   0.045       09440.997   0.045       010643.84   0.045       0
#XS Ineff= 2 , 0
       09853.963        10073.28       0
Bank Sta=9440.997,10643.84
Exp/Cntr=0.3,0.1

Type RM Length L Ch R = 1 ,4988.907,143.688400,143.688400,143.688400
XS GIS Cut Line= 6
1263227.42747894617809.1699598881263087.68344975617811.407600775
1262729.16173425617807.1240535231262637.90302226617814.374690682
1262479.53901902617835.8054506781262196.98693565617881.378367335
#Sta/Elev= 30
9460.092123.06129549.375118.60699569.063118.74039592.032122.3167 9631.41121.0733
9677.353123.13539703.606121.28139762.675120.47959779.083121.76399805.335121.1737
9818.462122.07979844.715120.52319903.787 120.7439953.025119.33249966.178  116.04
 10002.4110.760210022.14116.308110032.01117.709810084.87119.127710111.35117.6503
10127.91120.408610144.46120.028110151.08121.2795 10157.7120.487910194.12121.7877
10240.59119.885910290.43122.911310410.07118.621810449.95120.920610496.04  120.17
#Mann= 3 , 0 , 0
9460.092   0.045       09460.092   0.045       010496.04   0.045       0
#XS Ineff= 2 , 0
       09863.673        10065.56       0
Bank Sta=9460.092,10496.04
Exp/Cntr=0.3,0.1

Type RM Length L Ch R = 1 ,4845.219,169.017900,169.017900,169.017900
XS GIS Cut Line= 6
1263223.71322954 617690.147922651263083.33590898617687.055178955
1262811.95571014617669.0796787441262682.79155326617667.413858816
1262546.93184775617665.9689266981262196.69758379617776.090462252
#Sta/Elev= 30
9454.802120.60089504.283117.71929543.663116.93989592.887 112.9879612.611113.2476
9635.627115.15619714.539115.44239730.979117.96279836.196 115.6469859.212116.7834
9869.072115.53219937.976113.43529964.224110.72889987.192 110.93310006.88109.3423
10042.97113.4776 10072.5111.529310082.34112.937910108.59113.295410141.84115.5992
10179.67113.515610231.26114.0781 10251.9116.586310282.85118.322410368.83116.9904
10403.22 120.67510420.42117.811910451.37116.6674   10472 117.81410499.37116.8304
#Mann= 3 , 0 , 0
9454.802   0.045       09454.802   0.045       010499.37   0.045       0
#XS Ineff= 2 , 0
       09858.201        10051.03       0
Bank Sta=9454.802,10499.37
Exp/Cntr=0.3,0.1

Type RM Length L Ch R = 1 ,4676.201,146.946300,146.946300,146.946300
XS GIS Cut Line= 6
 1263238.3905634617601.9807675781262905.53083494617564.425804466
1262546.94628671617452.2893005011262357.51613134617421.986046851
1262284.87676132617415.3071416911261857.14318568617447.784617335
#Sta/Elev= 30
9458.802122.50669565.748115.26189618.472114.60619634.948112.97099678.011 112.627
9714.454110.60499811.437112.98079949.815108.198910001.28101.265810022.04104.7309
10056.64  107.3610115.28107.624110193.04105.439310233.18107.731310259.75106.3488
10289.65107.608510316.14106.485610477.66107.237410503.98105.811710517.14107.2521
10543.46 104.87610569.79 105.37510592.82 107.57910609.27106.4093 10632.3107.5404
10704.69106.964110721.14108.945710763.91108.530910790.24 110.73910864.11112.9997
#Mann= 3 , 0 , 0
9458.802  0.0553       09458.802  0.0553       010864.11  0.0553       0
#XS Ineff= 2 , 0
       09843.714        10066.33       0
Bank Sta=9458.802,10864.11
Exp/Cntr=0.3,0.1

Type RM Length L Ch R = 1 ,4529.254,172.869400,172.869400,172.869400
XS GIS Cut Line= 6
1263300.13937929617446.8186675161263002.17930329617425.536094368
 1262629.8683469617332.3541309091262502.02211511617312.064595982
 1262351.9348523 617311.06586735 1261879.2786023617343.617950663
#Sta/Elev= 30
9463.638137.99489556.769123.98619678.467 112.6859757.808107.12749814.359 106.823
9871.347103.86739901.782105.89159915.352103.69899946.005103.78739980.271101.5528
10082.82101.103910153.66103.888110180.37101.999110230.17103.630610246.74101.8044
10279.84103.571510365.15102.389510394.67102.661210411.08 104.54510470.24103.6312
10489.97104.841110503.12102.941210572.18102.117710618.22104.193710647.82103.1673
10726.75105.328310743.19103.609510766.21104.6272 10799.1 103.15210900.08106.3337
#Mann= 3 , 0 , 0
9463.638  0.0559       09463.638  0.0559       010900.08  0.0559       0
#XS Ineff= 2 , 0
       09913.444         10112.7       0
Bank Sta=9463.638,10900.08
Exp/Cntr=0.3,0.1

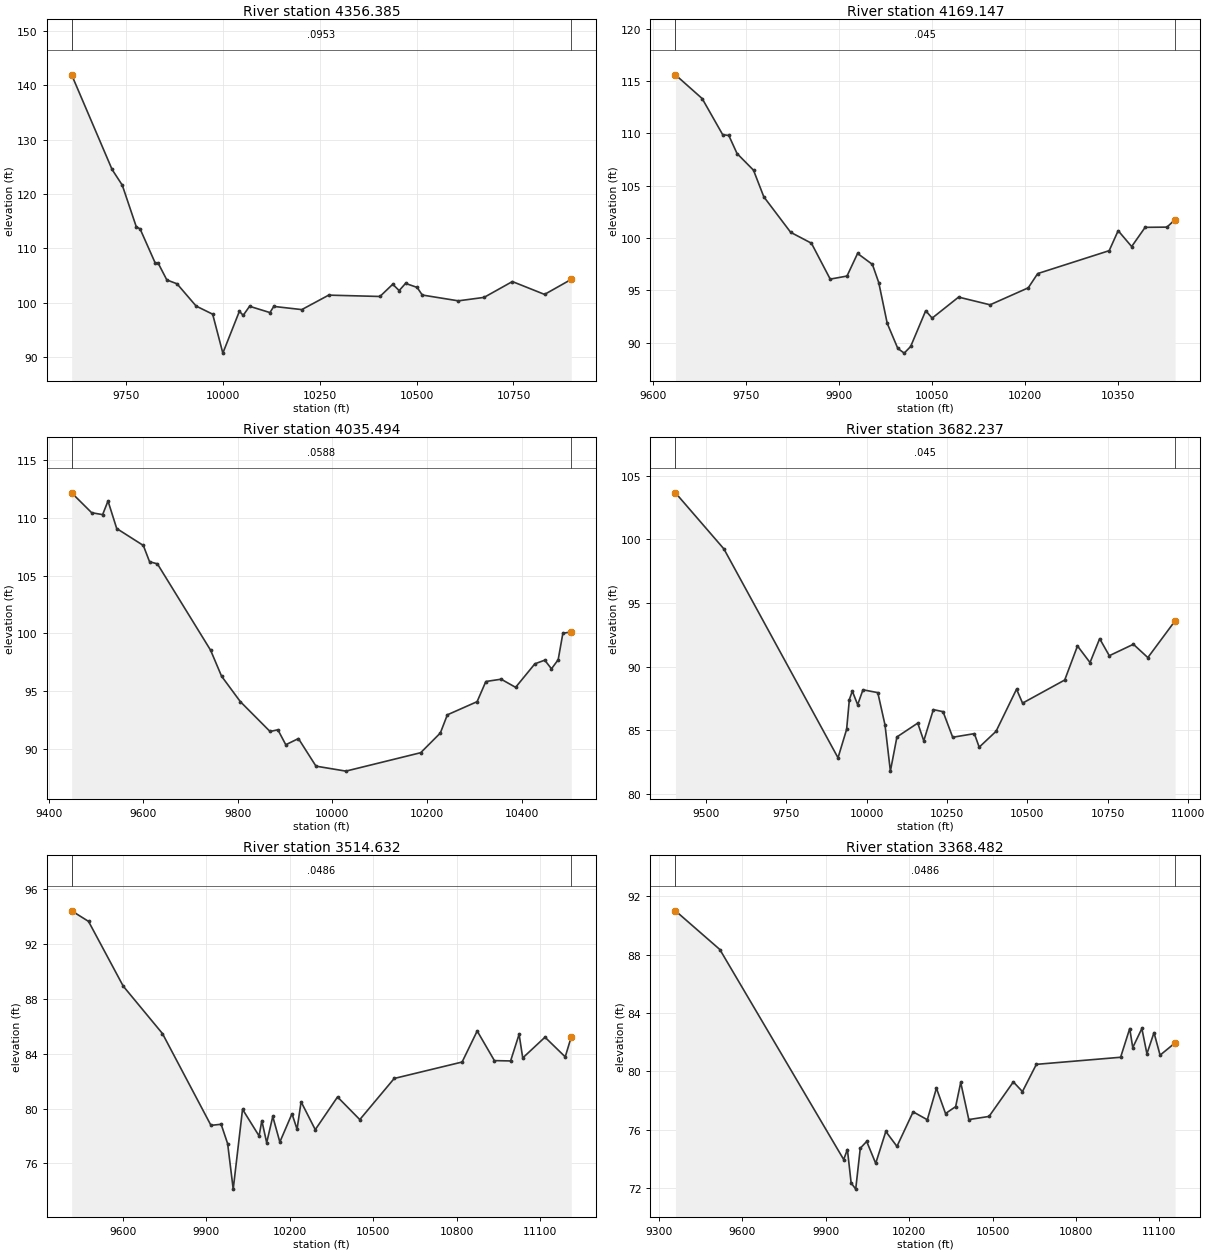
Type RM Length L Ch R = 1 ,4356.385,187.238000,187.238000,187.238000
XS GIS Cut Line= 6
1263186.57026902617192.5762840061262857.87578261617203.597691447
1262753.17926106617202.9865292161262590.46620834617210.130947009
1262314.17443568617242.0554506631261905.32026899617304.555450663
#Sta/Elev= 30
9610.915141.94169715.163 124.5149741.425121.62779777.534113.96799787.382113.5709
9826.774107.22649833.339107.35019856.318104.1767 9882.58103.4643 9931.8299.36757
9974.47697.8698610000.7290.6998410043.3898.4024710053.2397.6576310069.6599.32438
10122.1998.1659210132.04  99.30110204.2998.7136610273.63 101.37910405.74101.1304
10438.76103.382910455.28102.215610471.79103.540610501.59   102.810514.87101.3983
 10607.8100.327610674.18100.961610747.19103.877210830.17 101.511 10899.1 104.286
#Mann= 3 , 0 , 0
9610.915  0.0953       09610.915  0.0953       0 10899.1  0.0953       0
#XS Ineff= 2 , 0
       0 9889.99        10075.12       0
Bank Sta=9610.915,10899.1
Exp/Cntr=0.3,0.1

Type RM Length L Ch R = 1 ,4169.147,133.653500,133.653500,133.653500
XS GIS Cut Line= 6
1263112.05307809616955.1500623231263022.57741016616965.934057832
1262905.83868596616985.6539526581262755.28901029617025.792312801
  1262690.404181617048.0088650291262352.94758379617206.429003924
#Sta/Elev= 30
9636.608 115.5849679.713113.31839712.759109.87399722.673109.79289735.932108.0708
9762.488106.47969779.086103.94129822.402100.55069855.88399.510139886.19296.08088
9913.26796.374459930.33798.531569954.23597.484749964.47795.749539978.13391.86023
9995.204 89.464210005.5289.0162110015.9289.6498810040.19 93.0666 10050.692.35854
10093.2394.3648710143.9793.6293910205.5995.2509610220.7896.6097510336.0798.79719
10350.56100.706910372.31 99.191110394.06101.025310429.23101.045510442.37101.7665
#Mann= 3 , 0 , 0
9636.608   0.045       09636.608   0.045       010442.37   0.045       0
#XS Ineff= 2 , 0
       09930.059        10062.27       0
Bank Sta=9636.608,10442.37
Exp/Cntr=0.3,0.1

Type RM Length L Ch R = 1 ,4035.494,353.256800,353.256800,353.256800
XS GIS Cut Line= 6
1263272.00140321616810.3786566851262836.88855603616866.802267805
1262765.27397272616880.9081705961262689.31911159616910.205045596
1262596.00313938616951.4376844761262275.90765327617118.538378924
#Sta/Elev= 30
9448.669112.15399491.003110.43359514.161110.27029525.548111.44849543.936 109.068
9600.177107.60639613.411106.19659629.952106.01639742.43498.550759765.59296.30818
9805.29294.10747 9868.1591.525569884.69191.674459901.38190.380999928.13290.91401
9965.23388.5302910028.4588.0998410186.6189.6917610228.1591.3933610242.9592.96553
10305.8794.1030410324.3795.8464910356.7696.0459310387.2995.34159   1042897.37459
10448.9397.69118 10463.196.9409710477.2897.7276210487.22100.012910505.03100.1357
#Mann= 3 , 0 , 0
9448.669  0.0588       09448.669  0.0588       010505.03  0.0588       0
#XS Ineff= 2 , 0
       0 9919.18        10060.56       0
Bank Sta=9448.669,10505.03
Exp/Cntr=0.3,0.1

Type RM Length L Ch R = 1 ,3682.237,167.604400,167.604400,167.604400
XS GIS Cut Line= 6
1263282.32069638616617.0181084421262921.60069594616626.271618828
1262754.42327824616548.8769205961262674.12813938616543.451573372
1262605.76876435616598.7901150291261873.00690094617002.971249282
#Sta/Elev= 30
9405.259103.66679556.03699.257819910.88982.84802 9937.6485.082529946.14287.42349
9955.34788.089089971.97787.018329988.48388.19172 10034.687.96856   10057 85.4363
10073.7581.8009910094.1184.4872610158.8685.5744110177.5984.1815510207.3686.63444
10237.5486.4718710267.5284.4623210334.9684.7458810349.9583.68205 10402.484.92802
 10466.188.2392410484.8387.1438610615.9788.9599610655.6891.6347510694.6690.33085
10724.6392.20897 10754.690.8693610829.5491.76737 10874.590.7215610959.2593.61041
#Mann= 3 , 0 , 0
9405.259   0.045       09405.259   0.045       010959.25   0.045       0
#XS Ineff= 2 , 0
       09940.647        10072.11       0
Bank Sta=9405.259,10959.25
Exp/Cntr=0.3,0.1

Type RM Length L Ch R = 1 ,3514.632,146.150200,146.150200,146.150200
XS GIS Cut Line= 6
1263297.29361615616407.5864949971262883.31524622616399.950498343
1262779.81284267 616389.86015591  1262666.861397616367.351382777
1262609.67501438616370.9255316851261612.59023428616848.891388178
#Sta/Elev= 30
9415.65394.409959476.36793.640029601.04288.923759742.16885.464689916.50278.77606
9953.06578.85553 9976.4677.441439996.51374.1294310030.0179.9469210089.5378.00384
10099.3979.1195610116.8577.5086810138.6879.4233710164.1577.5613210207.8179.62059
   1022678.4928110240.5580.4931810291.4978.4632710371.5380.8456510451.5879.19612
10575.2882.1938510819.3783.3908610873.62 85.653610935.4783.4954510993.6883.47008
 11024.385.4125711037.3483.6889911117.39 85.201111190.1583.7667211211.9685.23718
#Mann= 3 , 0 , 0
9415.653  0.0486       09415.653  0.0486       011211.96  0.0486       0
#XS Ineff= 2 , 0
       09882.583        10121.32       0
Bank Sta=9415.653,11211.96
Exp/Cntr=0.3,0.1

Type RM Length L Ch R = 1 ,3368.482,245.154000,245.154000,245.154000
XS GIS Cut Line= 6
1263373.24847726616273.0378838861262959.27010734616265.401887231
1262855.76770378616255.3115447991262742.81625811616232.802771666
1262685.62987549616236.3769205741261688.54509539616714.342777067
#Sta/Elev= 30
9360.14791.007129519.78588.353939964.96973.951949978.36274.637579991.75672.34747
10008.2271.9218910024.6674.7249810047.6775.1943210080.0973.6894510116.4775.87719
10156.4974.85263 10214.777.2217410265.6476.6800710298.3978.8450210331.1377.10615
10367.5177.5798710385.7179.2371610414.8176.6911310487.5876.90756 10574.979.27529
10607.6478.6101310657.69 80.478910960.5680.96509 10993.382.9343111004.2281.62718
11036.9682.9380411055.1581.2036411080.6282.6549711102.4581.1096411156.4581.94983
#Mann= 3 , 0 , 0
9360.147  0.0486       09360.147  0.0486       011156.45  0.0486       0
#XS Ineff= 2 , 0
       09863.187        10167.02       0
Bank Sta=9360.147,11156.45
Exp/Cntr=0.3,0.1

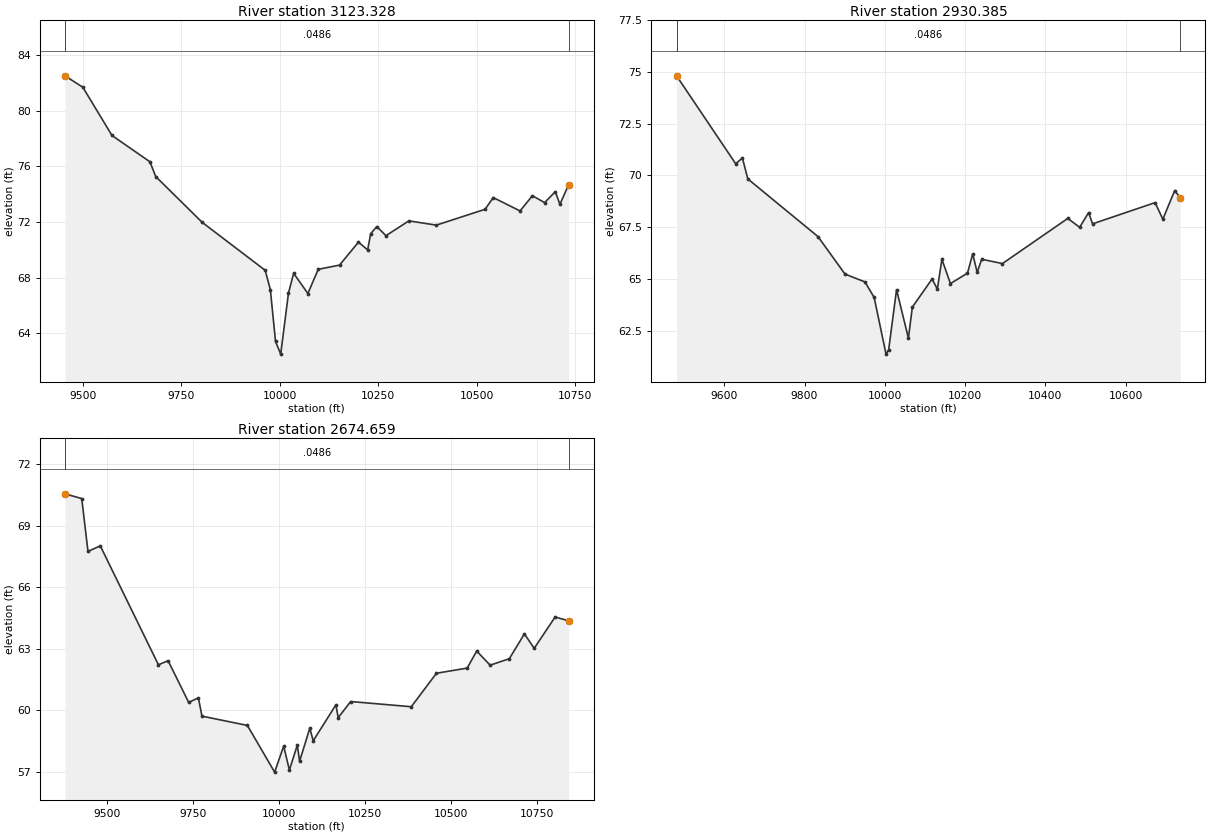
Type RM Length L Ch R = 1 ,3123.328,192.942600,192.942600,192.942600
XS GIS Cut Line= 4
 1263264.3177352616086.9515348521262832.46009636615989.295284837
 1262619.7864852615991.4654237331262092.44273522616321.326534837
#Sta/Elev= 30
 9455.37 82.52189500.62681.703189574.62778.229379670.84176.338119685.62875.27214
9803.35671.980859963.174 68.52959976.29867.134039989.42263.4088710002.5562.49904
10022.2366.8890410035.3668.3139410071.4566.85936 10097.768.6011910151.7668.90183
10199.8370.5590110223.0469.9983510230.7871.1644210246.2671.6775610269.4871.02011
10327.5372.0856310397.1971.7797410521.0272.9200610541.5273.7638810609.5772.80167
10640.9873.8946310671.94 73.400610699.0374.1899610710.6473.2736110732.8374.68451
#Mann= 3 , 0 , 0
 9455.37  0.0486       0 9455.37  0.0486       010732.83  0.0486       0
#XS Ineff= 2 , 0
       09829.402        10188.63       0
Bank Sta=9455.37,10732.83
Exp/Cntr=0.3,0.1

Type RM Length L Ch R = 1 ,2930.385,255.726700,255.726700,255.726700
XS GIS Cut Line= 4
1263262.14759633615895.9793126431262830.28995752615798.323062629
1262617.61634633615800.4932015241262085.93231857  616078.2709793
#Sta/Elev= 30
9481.08474.815939628.38970.564749645.20770.842699658.66269.830319833.57367.04131
9900.84665.228679950.62764.850179973.594  64.09710003.1261.3578210009.6861.57097
10029.3764.47349 10058.962.1299510068.7463.6313410117.9664.9923110131.0864.50128
10142.3965.9429210163.6564.7702910206.1665.2725510219.22 66.210710230.3365.30655
10241.5865.9468610293.2565.7365610456.1267.9205710485.7467.4908410507.9568.20159
 10517.967.6584310673.7768.6840610693.0367.8818910722.6469.26784 10736.468.91739
#Mann= 3 , 0 , 0
9481.084  0.0486       09481.084  0.0486       0 10736.4  0.0486       0
#XS Ineff= 2 , 0
       09831.211        10230.48       0
Bank Sta=9481.084,10736.4
Exp/Cntr=0.3,0.1

Type RM Length L Ch R = 1 ,2674.659,0.000000,0.000000,0.000000
XS GIS Cut Line= 4
1263381.50523522615715.8577848371263012.58162412615572.628618181
1262569.87329078615524.8855626431262066.40106857615891.639034852
#Sta/Elev= 30
9378.70470.545319427.43870.314289445.56867.739279481.37768.009519650.30862.21555
9678.46462.413889738.29460.381849766.44960.602369776.84859.713499908.84259.26117
9988.03956.9853910014.4458.2516110030.9457.0863610054.0458.3010310060.6457.51446
10090.33 59.127110100.2358.5133910166.23 60.263210172.8359.6395810209.1360.42522
10385.2960.17166 10458.461.8027510547.6562.0538710575.4162.8849410614.4262.19671
10670.1462.5109110714.0763.7209310742.4863.0178110803.3764.5439710842.6264.35769
#Mann= 3 , 0 , 0
9378.704  0.0486       09378.704  0.0486       010842.62  0.0486       0
#XS Ineff= 2 , 0
       09837.956        10298.51       0
Bank Sta=9378.704,10842.62
Exp/Cntr=0.3,0.1